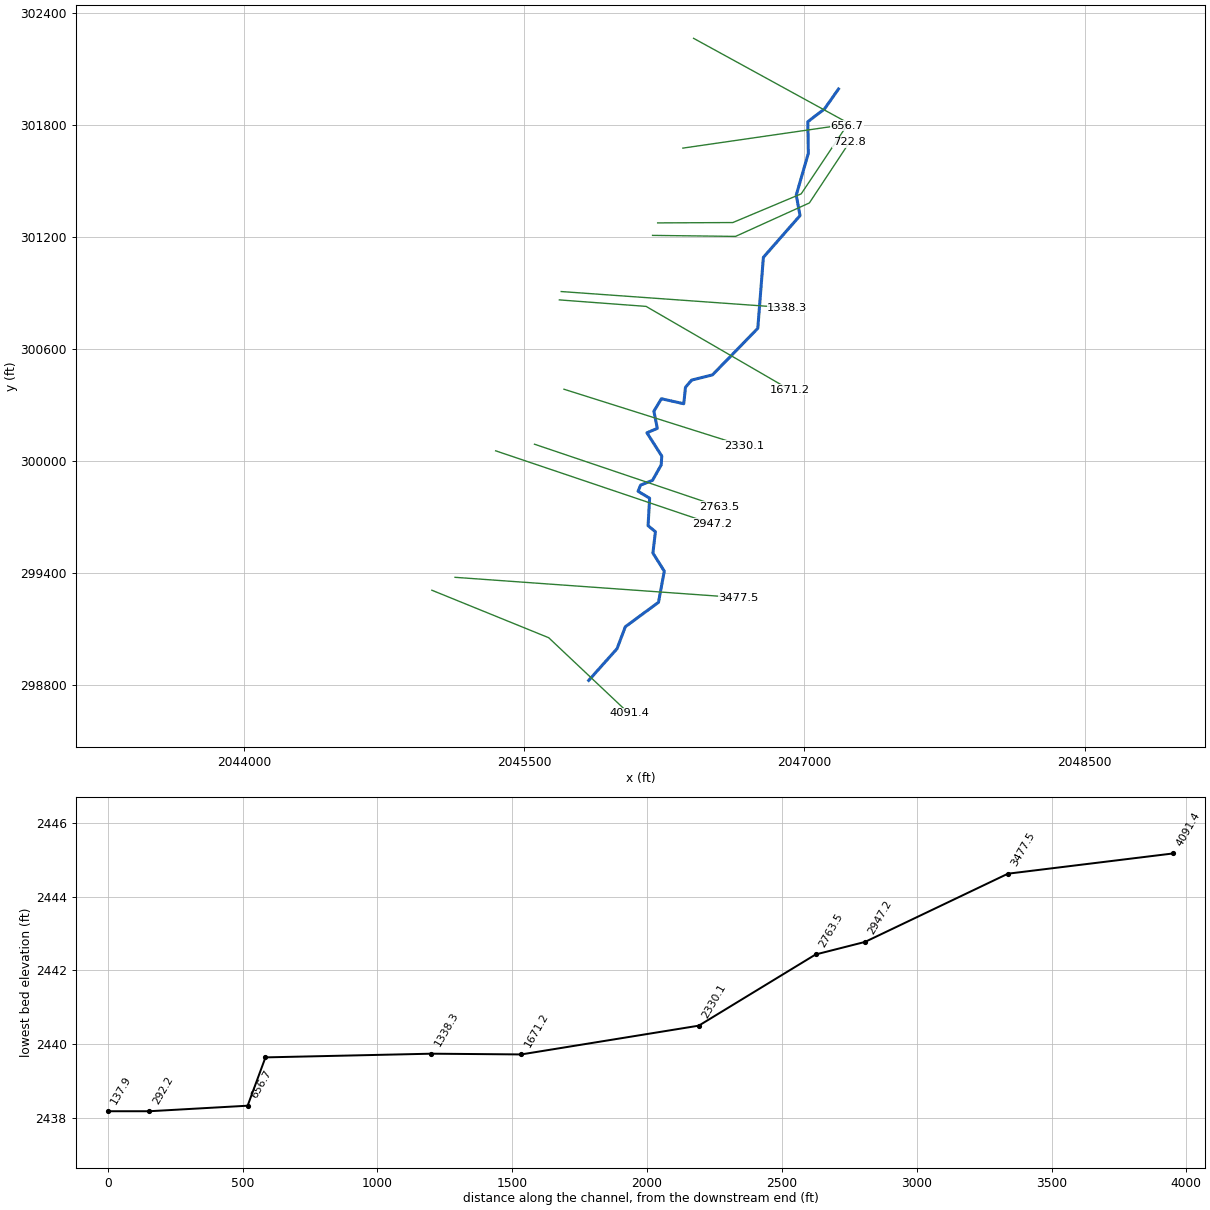
--- PattersnCk.prj (project) ---

Proj Title=PattersnCk
Current Plan=p01
Default Exp/Contr=0,0
English Units
Geom File=g01
Flow File=f01
Plan File=p01
BEGIN DESCRIPTION:
END DESCRIPTION:
DSS Export Rating Curves= 0
DSS Export Rating Curve Sorted= 0
DSS Export Volume Flow Curves= 0
DXF OffsetX= 0
DXF OffsetY= 0
DXF ScaleX= 0
DXF ScaleY= 0

--- PattersnCk.p01 (plan) ---

Plan Title=Floodplain
Program Version=4.00
Geom File=g01
Flow File=f01
K Sum by GR=0
Std Step Tol=0.01
Critical Tol=0.01
Num of Std Step Trials=20
Max Error Tol=0.3
Flow Tol Ratio=0.001
Split Flow NTrial=30
Split Flow Tol=0.02
Split Flow Ratio=0.02
Log Output Level=0
Friction Slope Method=1
Unsteady Friction Slope Method=2
Unsteady Bridges Friction Slope Method=1
Global Log Level=0
CheckData=False
Run HTab=0
Run UNet=0
Run PostProcess=0
UNET Theta=0
UNET Theta Warmup=0
UNET ZTol=0
UNET ZSATol=0
UNET MxIter=0
UNET MaxInSteps=0
UNET DtIC=0
UNET DtMin=0
UNET MaxCRTS=0
UNET WFStab=0
UNET SFStab=0
UNET WFX=0
UNET SFX=0
UNET DSS MLevel=0
UNET DZMax Abort=0
UNET Convert EG Bridges=0
UNET Use Existing IB Tables=0
UNET Froude Limit=0
UNET Froude Power=0
Write IC File=0
Echo Input=False
Echo Output=False
Write Detailed=0

--- PattersnCk.f01 (steady flow) ---

Flow Title=NFF Regression Equation
Program Version=4.00
Number of Profiles=1
Profile Names=P100yr
River Rch & RM=PattersnCk,Main      ,4091.4
606.2731
River Rch & RM=PattersnCk,Main      ,722.8
783.1192
River Rch & RM=PattersnCk,Main      ,722.8
641.7967
Boundary for River Rch & Prof#=PattersnCk,Main      ,1
Up Type=0
Dn Type=3
Dn Slope=0.006152

--- PattersnCk.g01 (geometry) ---

Geom Title=USGS 10m DEM
Program Version=4.10

River Reach=PattersnCk      ,Main
Reach XY= 30
     2045845.678      298823.029     2045997.342      298993.264
     2046041.706      299110.881     2046219.163       299241.91
     2046250.115       299409.05     2046189.243      299506.032
     2046202.656      299620.553      2046163.45      299652.537
     2046171.704      299800.074       2046109.8      299837.216
     2046123.213      299870.231      2046187.18      299896.025
     2046233.607      299978.563     2046236.703      300026.022
      2046157.26      300150.861     2046212.973      300174.591
     2046194.402      300266.414     2046234.639      300333.476
     2046354.319      300306.652     2046363.605       300395.38
      2046396.62      300433.554     2046508.047      300461.411
     2046750.503      300711.089     2046780.422      301091.796
     2046976.451       301315.68     2046956.278      301425.468
     2047020.964      301649.802     2047018.211      301819.084
     2047107.669      301887.898     2047182.396      301994.479

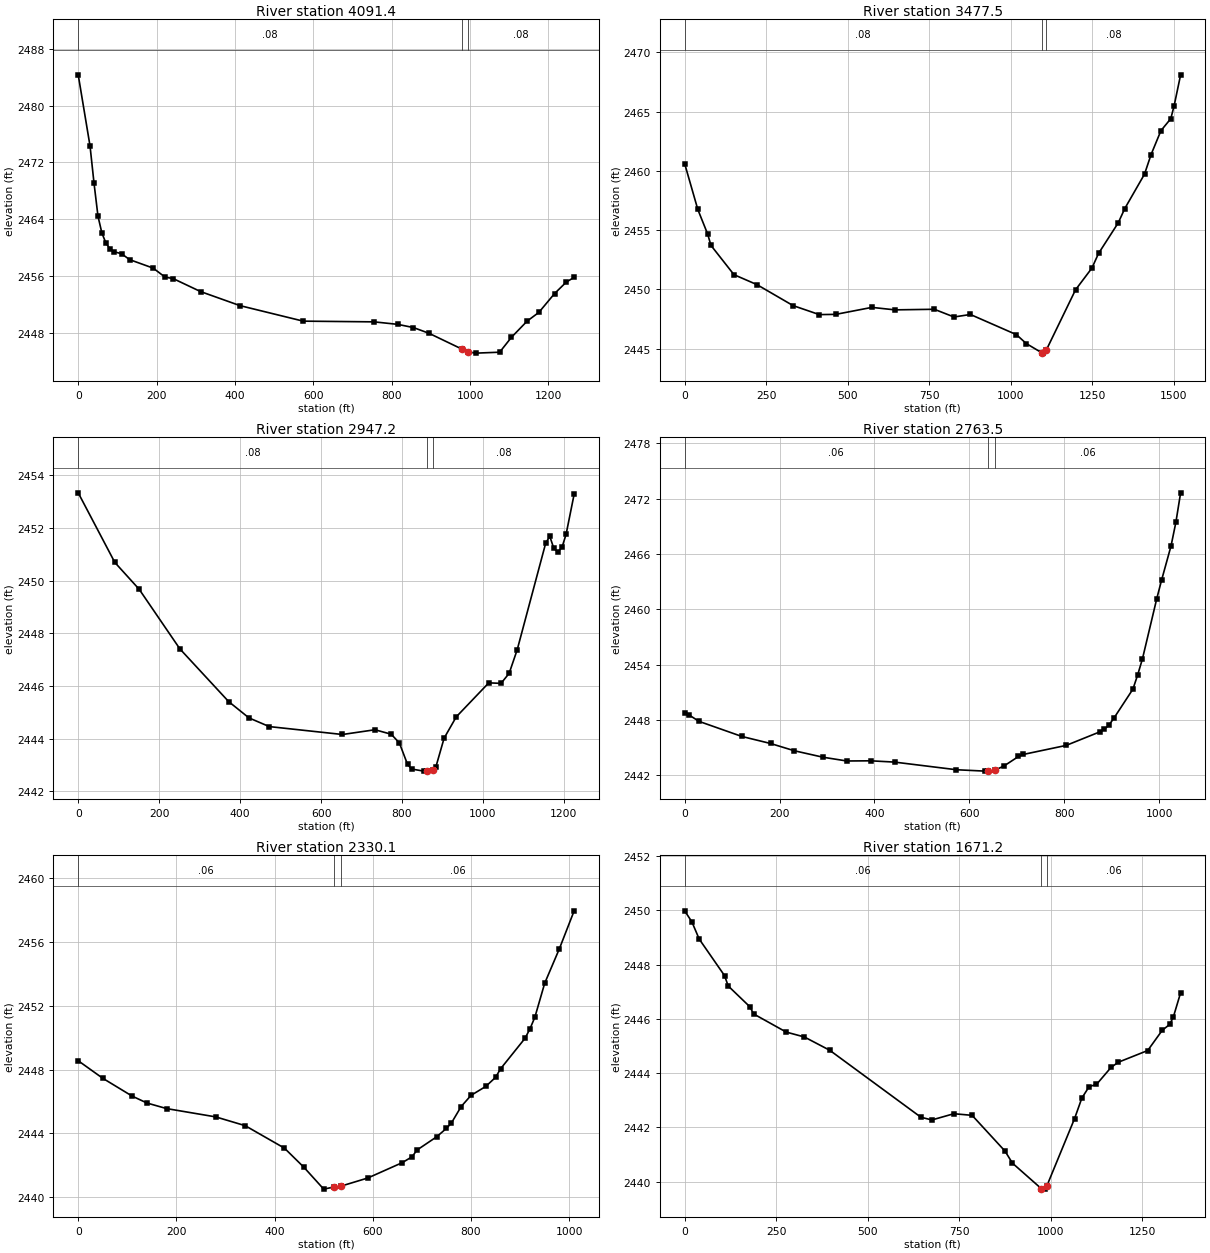
Type RM Length L Ch R = 1 ,4091.4  ,598.2,613.8,629.4
XS GIS Cut Line= 3
     2045006.482      299306.655     2045631.579      299051.986
     2046060.709      298646.293
#Sta/Elev= 30
       0 2484.33    30.2  2474.3    40.3  2469.1    50.4 2464.45    60.4 2462.07
    70.5 2460.69    80.6 2459.86    90.7 2459.45   110.8 2459.15     131 2458.33
   191.4 2457.13   221.6 2455.86   241.8 2455.67   312.3 2453.83     413 2451.85
   574.2 2449.67   755.1 2449.57   815.1 2449.22   855.2 2448.77   895.2 2447.96
   980.2 2445.71   995.2 2445.33  1015.3 2445.17  1075.4  2445.3  1105.4 2447.39
  1145.4 2449.67  1175.4  2450.9  1215.5 2453.55  1245.5 2455.17  1265.5 2455.83
#Mann= 3 , 0 , 0
       0     .08       0   980.2    .045       0   995.2     .08       0
Bank Sta=980.2,995.2
XS Rating Curve= 0 ,0
Exp/Cntr=0.3,0.1

Type RM Length L Ch R = 1 ,3477.5  ,534.4,530.1,523.6
XS GIS Cut Line= 2
     2045130.475      299375.878     2046648.396      299267.046
#Sta/Elev= 30
       0  2460.6    40.3 2456.74    70.6 2454.66    80.6 2453.71   151.2 2451.24
   221.7  2450.4   332.6 2448.63   413.2 2447.87   463.6 2447.89   574.5 2448.48
     645 2448.27     766 2448.32   826.4 2447.67   876.8 2447.88  1017.9 2446.18
  1048.1 2445.43  1095.2 2444.66  1098.5 2444.62  1110.2 2444.91  1199.3 2449.96
  1249.7  2451.8  1269.9 2453.03  1330.3 2455.61  1350.5 2456.82    1411 2459.72
  1431.1 2461.37  1461.4 2463.39  1491.6  2464.4  1501.7 2465.47  1521.8  2468.1
#Mann= 3 , 0 , 0
       0     .08       0  1095.2    .045       0  1110.2     .08       0
Bank Sta=1095.2,1110.2
XS Rating Curve= 0 ,0
Exp/Cntr=0.3,0.1

Type RM Length L Ch R = 1 ,2947.2  ,167.3,183.1,185.5
XS GIS Cut Line= 2
     2045347.736      300054.288     2046508.316      299661.501
#Sta/Elev= 30
       0 2453.33    90.4 2450.69   150.6 2449.67   251.1 2447.41   371.6 2445.41
   421.8 2444.79     472 2444.46   652.8 2444.16   733.1 2444.34   773.3 2444.17
   793.4 2443.84   813.5 2443.03   823.5 2442.85   853.6 2442.77   860.5 2442.77
   875.5 2442.81   883.8 2442.94   903.9 2444.02     934 2444.83  1014.3 2446.12
  1044.5  2446.1  1064.6 2446.48  1084.6 2447.38  1154.9 2451.42    1165 2451.68
    1175 2451.22  1185.1 2451.09  1195.1 2451.26  1205.2 2451.75  1225.2 2453.28
#Mann= 3 , 0 , 0
       0     .08       0   860.5    .045       0   875.5     .08       0
Bank Sta=860.5,875.5
XS Rating Curve= 0 ,0
Exp/Cntr=0.3,0.1

Type RM Length L Ch R = 1 ,2763.5  ,468,433.3,428.9
XS GIS Cut Line= 2
     2045555.685      300089.658     2046545.592      299754.456
#Sta/Elev= 30
       0 2448.69      10  2448.5    30.2 2447.83   120.6 2446.19   180.9 2445.43
   231.1 2444.64   291.4 2443.94   341.7 2443.53   391.9 2443.55   442.2 2443.41
   572.8 2442.58   633.1 2442.43     639 2442.44     654 2442.54   673.3    2443
   703.4 2444.02   713.5 2444.24   803.9 2445.22   874.3 2446.68   884.3 2446.96
   894.4 2447.45   904.4 2448.17   944.6 2451.33   954.7 2452.89   964.7 2454.62
   994.9 2461.16  1004.9 2463.14    1025 2466.89  1035.1 2469.43  1045.1 2472.63
#Mann= 3 , 0 , 0
       0     .06       0     639    .045       0     654     .06       0
Bank Sta=639,654
XS Rating Curve= 0 ,0
Exp/Cntr=0.3,0.1

Type RM Length L Ch R = 1 ,2330.1  ,643.1,658.5,653.4
XS GIS Cut Line= 2
     2045713.082      300384.585     2046676.107      300079.918
#Sta/Elev= 30
       0 2448.55      50 2447.45     110 2446.33     140  2445.9     180 2445.55
     280 2445.03     340 2444.48     420 2443.07     460 2441.86     500  2440.5
   520.5 2440.63   535.5 2440.69     590  2441.2     660 2442.16     680 2442.53
     690 2442.95     730 2443.78     750 2444.31     760 2444.64     780 2445.68
   800.1 2446.38   830.1 2446.94   850.1 2447.51   860.1 2448.04   910.1 2449.96
   920.1 2450.55   930.1 2451.28   950.1 2453.41   980.1 2455.58  1010.1 2457.95
#Mann= 3 , 0 , 0
       0     .06       0   520.5    .045       0   535.5     .06       0
Bank Sta=520.5,535.5
XS Rating Curve= 0 ,0
Exp/Cntr=0.3,0.1

Type RM Length L Ch R = 1 ,1671.2  ,322.3,332.9,343.4
XS GIS Cut Line= 3
     2045688.744      300863.507     2046152.715      300828.709
     2046921.361      300382.136
#Sta/Elev= 30
       0 2449.98    19.8 2449.57    39.6 2448.94   108.9 2447.59   118.8 2447.21
   178.2 2446.44   188.1 2446.18   277.2 2445.51   326.7 2445.33     396 2444.84
   645.1 2442.37     675 2442.27     735  2442.5   784.9 2442.44   874.8 2441.12
   894.8 2440.68   973.7 2439.74   984.7 2439.72   988.7 2439.83  1064.6 2442.32
  1084.6 2443.08  1104.5  2443.5  1124.5 2443.58  1164.4 2444.21  1184.4  2444.4
  1264.3 2444.83  1304.3 2445.58  1324.3 2445.79  1334.2 2446.06  1354.2 2446.96
#Mann= 3 , 0 , 0
       0     .06       0   973.7    .045       0   988.7     .06       0
Bank Sta=973.7,988.7
XS Rating Curve= 0 ,0
Exp/Cntr=0.3,0.1

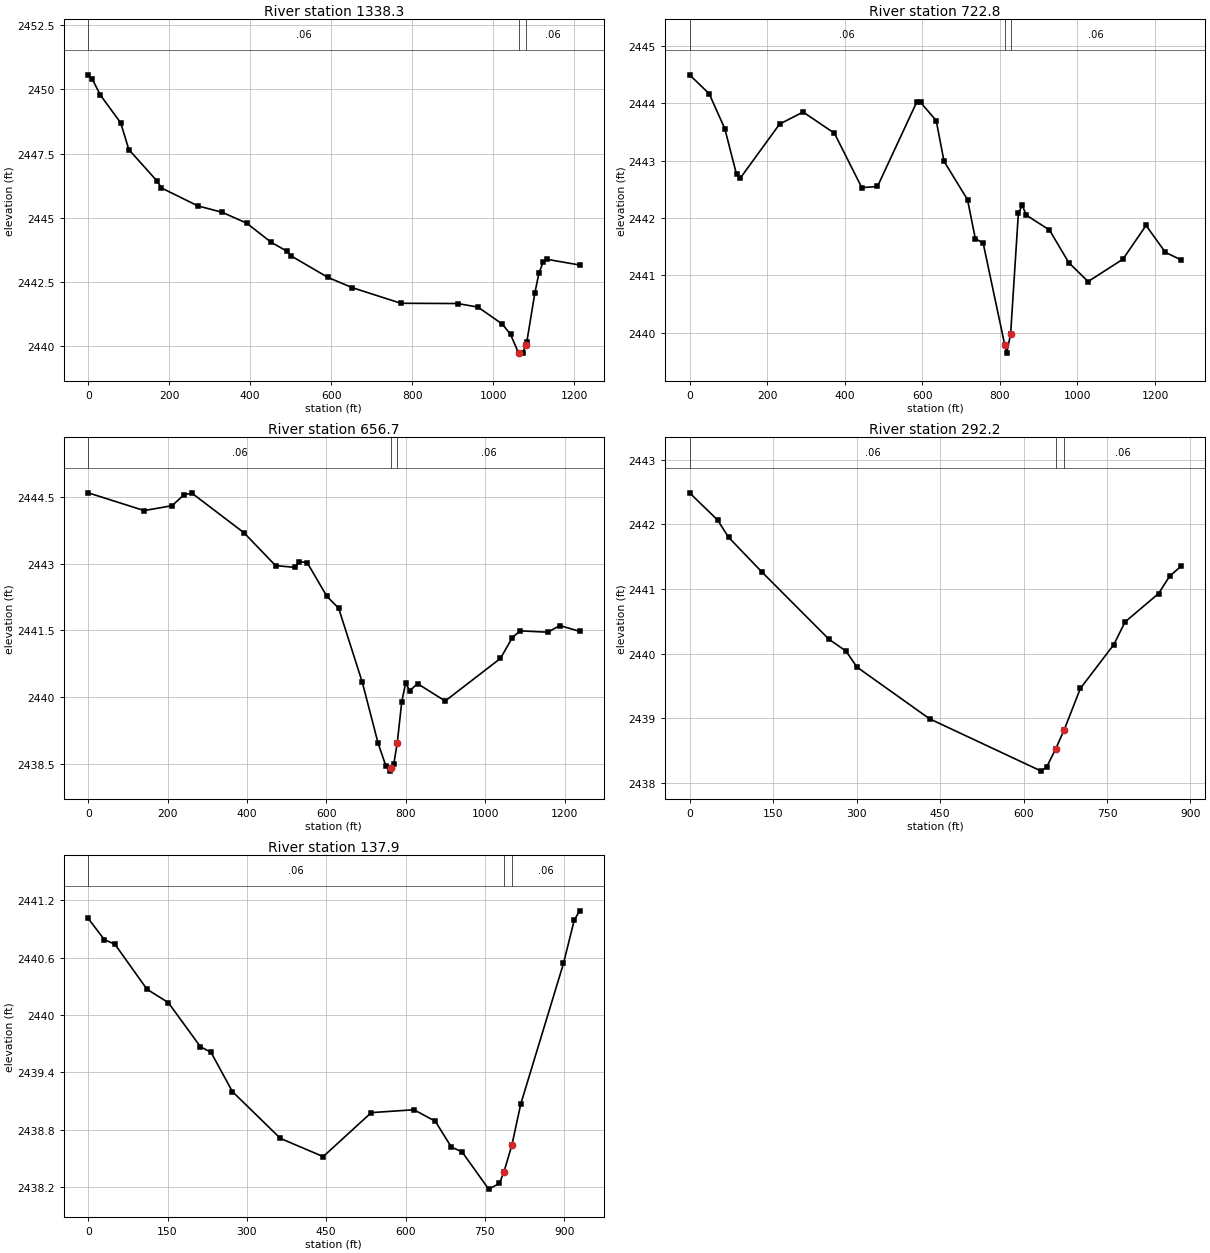
Type RM Length L Ch R = 1 ,1338.3  ,603.9,615.6,627
XS GIS Cut Line= 2
     2045698.572      300908.339     2046908.675      300821.616
#Sta/Elev= 30
       0 2450.57      10  2450.4    30.1 2449.78    80.2  2448.7   100.3 2447.66
   170.4 2446.43   180.5 2446.17   270.7 2445.47   330.9 2445.22     391  2444.8
   451.2 2444.06   491.3  2443.7   501.3 2443.52   591.6 2442.69   651.7 2442.29
     772 2441.68   912.4 2441.67   962.5 2441.53  1022.7 2440.87  1042.8 2440.47
  1062.8 2439.74  1064.9 2439.74  1072.8 2439.74  1079.9 2440.04  1082.9 2440.16
  1102.9 2442.08  1112.9 2442.84    1123 2443.27    1133 2443.39  1213.2 2443.17
#Mann= 3 , 0 , 0
       0     .06       0  1064.9    .045       0  1079.9     .06       0
Bank Sta=1064.9,1079.9
XS Rating Curve= 0 ,0
Exp/Cntr=0.3,0.1

Type RM Length L Ch R = 1 ,722.8   ,66.8,66.1,67.5
XS GIS Cut Line= 4
     2046187.384      301209.446     2046631.395      301204.009
     2047026.474      301383.426     2047240.324      301707.826
#Sta/Elev= 30
       0  2444.5    50.5 2444.17    90.8 2443.56   121.1 2442.76   131.2  2442.7
   232.1 2443.64   292.7 2443.85   373.4 2443.48     444 2442.53   484.4 2442.55
   585.3 2444.02   595.4 2444.02   635.8  2443.7     656 2442.99   716.5 2442.32
   736.7 2441.64   756.9 2441.56   812.6 2439.78   817.4 2439.64   827.6 2439.97
   847.7 2442.09   857.8 2442.22   867.9 2442.05   927.8 2441.79   977.6 2441.22
  1027.4 2440.89  1117.1 2441.28  1176.8 2441.87  1226.6  2441.4  1266.5 2441.27
#Mann= 3 , 0 , 0
       0     .06       0   812.6    .045       0   827.6     .06       0
Bank Sta=812.6,827.6
XS Rating Curve= 0 ,0
Exp/Cntr=0.3,0.1

Type RM Length L Ch R = 1 ,656.7   ,370.4,364.4,356.3
XS GIS Cut Line= 4
     2046214.568      301276.501     2046616.897      301278.313
     2046982.979      301432.358     2047225.826      301796.628
#Sta/Elev= 30
       0  2444.6   140.8  2444.2   211.2 2444.31   241.4 2444.56   261.5 2444.59
   392.3  2443.7   471.8 2442.96   521.5 2442.92   531.4 2443.05   551.3 2443.03
   600.9 2442.27   630.7    2442   690.3 2440.33     730 2438.96   749.9 2438.44
   759.8 2438.33   763.2 2438.39   769.7  2438.5   778.2 2438.96   789.6 2439.89
   799.5 2440.32   809.4 2440.14   829.4  2440.3     899 2439.91  1038.3 2440.87
  1068.2 2441.34    1088 2441.49  1157.7 2441.46  1187.6 2441.61  1237.3 2441.48
#Mann= 3 , 0 , 0
       0     .06       0   763.2    .045       0   778.2     .06       0
Bank Sta=763.2,778.2
XS Rating Curve= 0 ,0
Exp/Cntr=0.3,0.1

Type RM Length L Ch R = 1 ,292.2   ,168.9,154.3,139.7
XS GIS Cut Line= 2
     2046349.584       301677.47     2047223.107       301804.33
#Sta/Elev= 18
       0 2442.49    50.2 2442.07    70.2  2441.8   130.4 2441.26   250.8 2440.22
   280.9 2440.04   300.9 2439.79   431.3 2438.99   631.9 2438.18     642 2438.25
   658.1 2438.53   673.1 2438.82   702.1 2439.46   762.3 2440.14   782.4 2440.49
   842.6 2440.93   862.6  2441.2   882.7 2441.35
#Mann= 3 , 0 , 0
       0     .06       0   658.1    .045       0   673.1     .06       0
Bank Sta=658.1,673.1
XS Rating Curve= 0 ,0
Exp/Cntr=0.3,0.1

Type RM Length L Ch R = 1 ,137.9   ,143.4,137.8,132.1
XS GIS Cut Line= 2
     2046406.973      302266.162     2047221.295      301819.131
#Sta/Elev= 23
       0 2441.01    30.3 2440.79    50.5 2440.74   111.1 2440.27   151.5 2440.13
     212 2439.67   232.2 2439.61   272.6  2439.2   363.5 2438.71   444.3 2438.52
   535.2 2438.98   615.9 2439.01   656.3 2438.89   686.6 2438.62   706.8 2438.57
   757.3 2438.18   777.5 2438.24   786.1 2438.36   801.1 2438.64   817.9 2439.07
   898.7 2440.54   918.9 2440.99     929 2441.09
#Mann= 3 , 0 , 0
       0     .06       0   786.1    .045       0   801.1     .06       0
Bank Sta=786.1,801.1
XS Rating Curve= 0 ,0
Exp/Cntr=0.3,0.1

Chan Stop Cuts=-1
Use User Specified Reach Order=0
Composite Channel Slope=5